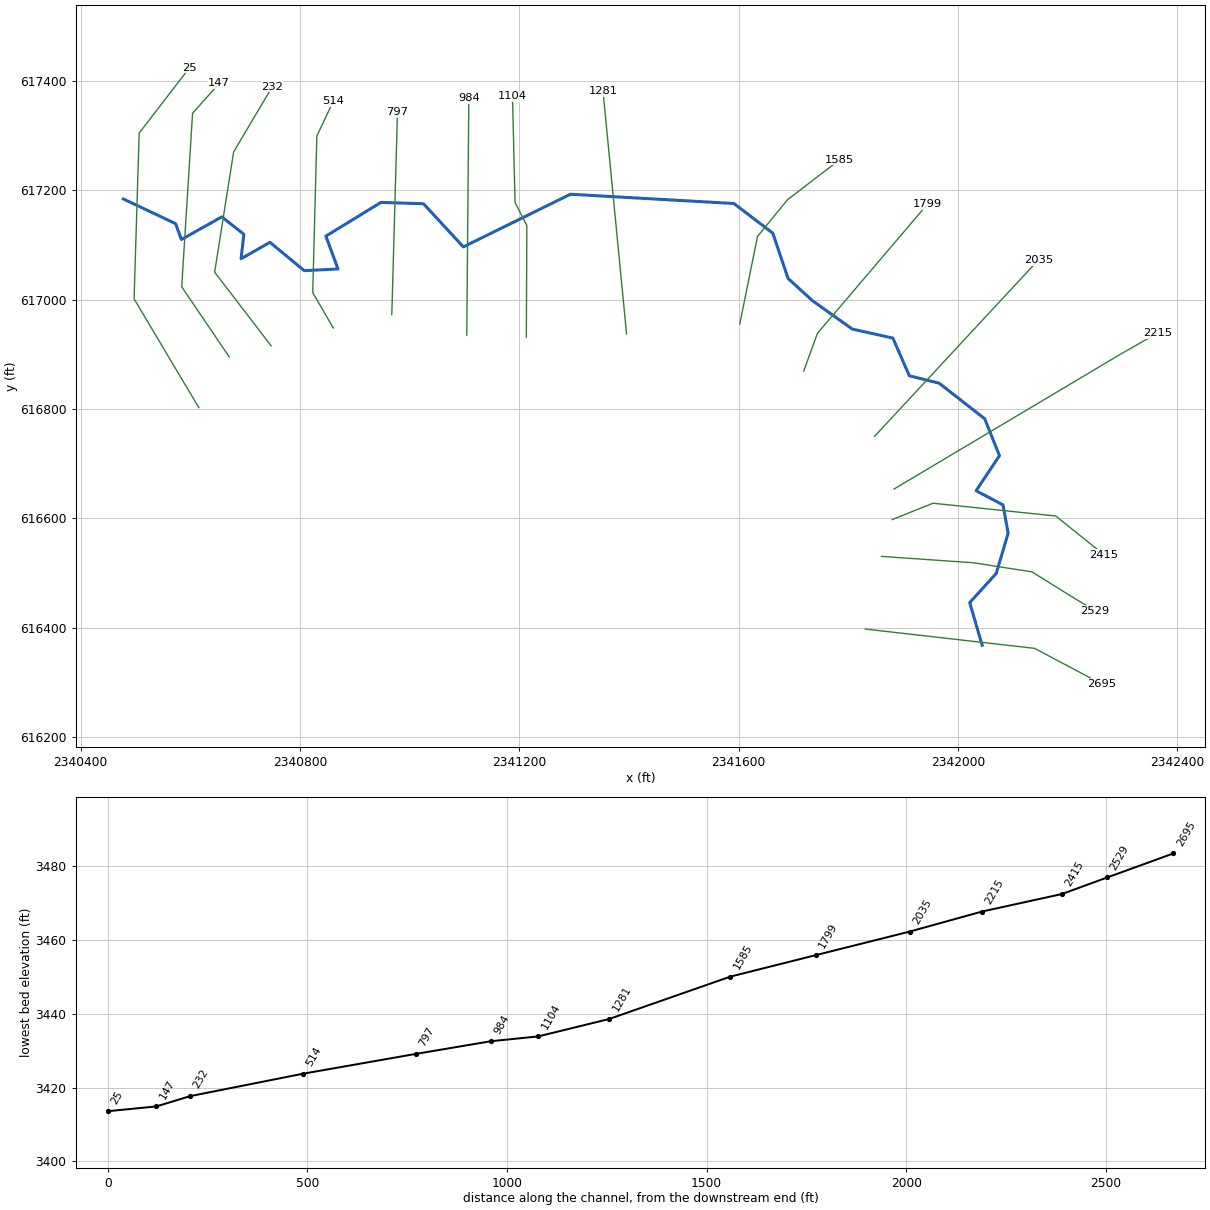
--- LAURELFKT5.prj (project) ---

Proj Title=LAURELFKT5
Current Plan=p01
Default Exp/Contr=0,0
English Units
Geom File=g01
Flow File=f01
Plan File=p01
Background Map Layer=Inundation Boundary (P100yr Value_0)
BEGIN DESCRIPTION:
----------MODEL BY WOOD PLC 2022----------
AFH study
Randolph County, WV
HEC-RAS Version: RAS 6.2
Vertical Datum: NAVD88
Projection: NAD 1983 StatePlane West Virginia S FIPS 4702 (US Feet)
Terrain: 1-meter LIDAR (FEMA Region III 3DEP collected 2016-2018)
Land Use: 2019 NLCD
Hydrologic Method:
WV SIR2010-5033 regression equations
Additional Model Notes:
None
END DESCRIPTION:
DSS Export Rating Curves= 0
DSS Export Rating Curve Sorted= 0
DSS Export Volume Flow Curves= 0
DXF OffsetX= 0
DXF OffsetY= 0
DXF ScaleX= 0
DXF ScaleY= 0

--- LAURELFKT5.p01 (plan) ---

Plan Title=Floodplain
Program Version=6.20
Short Identifier=Floodplain
Geom File=g01
Flow File=f01
Subcritical Flow
K Sum by GR= 0
Std Step Tol= 0.01
Critical Tol= 0.01
Num of Std Step Trials= 20
Max Error Tol= 0.3
Flow Tol Ratio= 0.001
Split Flow NTrial= 30
Split Flow Tol= 0.02
Split Flow Ratio= 0.02
Log Output Level= 0
Friction Slope Method= 1
Unsteady Friction Slope Method= 2
Unsteady Bridges Friction Slope Method= 1
Parabolic Critical Depth
Global Vel Dist= 0 , 0 , 0
Global Log Level= 0
CheckData=False
Encroach Param=-1 ,0,0, 0
Mapping Interval=1HOUR
Computation Time Step Use Courant=        0
Computation Time Step Use Time Series=    0
Computation Time Step Count To Double=0
Computation Time Step Max Doubling=0
Computation Time Step Max Halving=0
Computation Time Step Residence Courant=0
Run HTab= 0
Run UNet= 0
Run Sediment= 0
Run PostProcess= 0
Run WQNet= 0
Run RASMapper=-1
UNET Theta= 0
UNET Theta Warmup= 0
UNET ZTol= 0
UNET ZSATol= 0
UNET MxIter= 0
UNET Max Iter WO Improvement= 0
UNET MaxInSteps= 0
UNET DtIC= 0
UNET DtMin= 0
UNET MaxCRTS= 0
UNET WFStab= 0
UNET SFStab= 0
UNET WFX= 1
UNET SFX= 1
UNET Gravity=32.174
UNET 1D Methodology=Finite Difference
UNET DSS MLevel= 1
UNET Pardiso=0
UNET DZMax Abort= 0
UNET Use Existing IB Tables= 0
UNET Froude Reduction=False
UNET Froude Limit= 0
UNET Froude Power= 0
UNET D1 Cores= 0
UNET WindReference=Eulerian
UNET WindDragFormulation=Hsu (1988)
UNET D2 Coriolis=0
UNET D2 Cores= 0
UNET D2 Theta= 1
UNET D2 Theta Warmup= 1
UNET D2 Z Tol= 0.01
UNET D2 Volume Tol= 0.01
UNET D2 Max Iterations= 20
UNET D2 Equation= 0
UNET D2 RampUpFraction=0.1
UNET D2 TimeSlices= 1
UNET D2 Turbulence Formulation=Non-Conservative (original)
UNET D2 Eddy Viscosity=0.3
UNET D2 Transverse Eddy Viscosity=0.1
UNET D2 Smagorinsky Mixing=0
UNET D2 BCVolumeCheck=0
UNET D2 Cores=0
UNET D2 SolverType=PARDISO (Direct)
UNET D2 Minimum Iterations= 2147483647
UNET D2 Maximum Iterations= 2147483647
UNET D2 Restart Number= 10
UNET D2 Relaxation Coeff=1.3
UNET D2 SOR Precondition Iterations= 10
UNET D2 ILUT Maximum Fill= 8
UNET D2 ILUT Tolerance=1E-08
UNET D1D2 MaxIter= 0
UNET D1D2 ZTol=0.01
UNET D1D2 QTol=0.1
UNET D1D2 MinQTol=1
Write IC File= 0
Write IC File at Fixed DateTime=0
Write IC File at Sim End=0
Echo Input=False
Echo Parameters=False
Echo Output=False
Write Detailed= 0
HDF Write Warmup=0
HDF Write Time Slices=0
HDF Flush=0
HDF Compression= 1
HDF Chunk Size= 1
HDF Spatial Parts= 1
HDF Use Max Rows=0
HDF Fixed Rows= 1
Calibration Method= 0
Calibration Iterations= 20
Calibration Max Change=0.05
Calibration Tolerance=0.2
Calibration Maximum=1.5
Calibration Minimum=0.5
Calibration Optimization Method= 1
WQ AD Non Conservative
WQ ULTIMATE=-1
WQ Max Comp Step=1HOUR
WQ Output Interval=15MIN
WQ Output Selected Increments= 0
WQ Output face flow=0
WQ Output face velocity=0
WQ Output face area=0
WQ Output face dispersion=0
WQ Output cell volume=0
WQ Output cell surface area=0
WQ Output cell continuity=0
WQ Output cumulative cell continuity=0
WQ Output face conc=0
WQ Output face dconc_dx=0
WQ Output face courant=0
WQ Output face peclet=0
WQ Output face adv mass=0
WQ Output face disp mass=0
WQ Output cell mass=0
WQ Output cell source sink temp=0
WQ Output nsm pathways=0
WQ Output nsm derived pathways=0
WQ Create Restart=0
WQ Fixed Restart=0
WQ System Summary=0
WQ Write To DSS=0
Sorting and Armoring Iterations= 10
XS Update Threshold= 0.02
Bed Roughness Predictor= 0
Hydraulics Update Threshold= 0.02
Energy Slope Method= 1
Volume Change Method= 1
Sediment Retention Method= 0
Sediment TS Multiplier= 1
Warm Up Method= 0
XS Weighting Method= 0
Number of US Weighted Cross Sections= 1
Number of DS Weighted Cross Sections= 1
Upstream XS Weight=0
Main XS Weight=1
Downstream XS Weight=0
Number of DS XS's Weighted with US Boundary= 1
Upstream Boundary Weight= 1
Weight of XSs Associated with US Boundary= 0
Number of US XS's Weighted with DS Boundary= 1
Downstream Boundary Weight= 0.5
Weight of XSs Associated with DS Boundary= 0.5
Percentile Method= 0
Sediment Output Level= 3
Mass or Volume Output= 0
Output Increment Type= 1
Profile and TS Output Increment= 1
Transport Output Increment 1
XS Output Flag= 0
XS Output Increment= 10
Read HDF5 Sediment Hotstart= 0
Sediment Hotstart Type= 0
Write Gradation File= 0
Read Gradation Hotstart= 0
Write HDF5 File= 1
Write Binary Output= 1
Write DSS Sediment File= 0
DSS Sediment Output Type= 1
SV Curve= 0
Specific Gage Flag= 0
Subcell Erosion Methods= 0
Subcell Deposition Methods= 0
Advection Scheme= 1
Matrix Solver= 0
Implicit Weighting Factor= 1
Maximum Outer Loop Convergence Iterations= 5
Convergence Maximum Absolute= 0.001
Convergence RMSE= 0.0001
Grain Fractions Max Abs Error= 0.001
Max Subgrid Regions= 1
Max Subgrid Length Scale= 3.402823E+38
Initial Layer Thickness= 3.402823E+38
Min Layer Thickness= 3.402823E+38
Max Layer Thickness= 3.402823E+38
Number of Layers= 5

--- LAURELFKT5.f01 (steady flow) ---

Flow Title=Flow
Program Version=6.20
Number of Profiles= 1
Profile Names=P100yr
River Rch & RM=LAURELFKT5,Main,2695
     163
River Rch & RM=LAURELFKT5,Main,1281
     227
Boundary for River Rch & Prof#=LAURELFKT5,Main            , 1
Up Type= 0
Dn Type= 3
Dn Slope=0.01064
DSS Import GetInterval= 0
DSS Import GetPeak= 0
DSS Import FillOption= 0

--- LAURELFKT5.g01 (geometry) ---

Geom Title=Geometry
Program Version=6.20

River Reach=LAURELFKT5      ,Main
Reach XY= 30
 2342044.2662318616367.8481204932342021.54655871616445.898262122
 2342069.9063759616499.264244186  2342091.627006616573.060118767
2342082.24913638616624.7489757382342033.21650102616650.616625748
2342075.82175053616714.6698732512342048.95644718616782.254274746
2341965.78900002616847.3980000172341911.44299999616860.937000021
2341881.40800001616929.899000019     2341807.412616946.455000013
2341734.88800001616998.231999993     2341690.331617039.035999998
2341662.37051248617121.9731131772341591.51392454617176.176770316
     2341293.315617193.1710000192341098.03577093617096.786097546
2341025.35600004617175.7310000062340947.69600002617178.196999997
2340847.36199712617116.4851722972340869.43800002617056.357999995
2340807.81582156617053.3564149892340745.35100001      617105.213
2340692.69700001617075.1250000152340697.77500001617119.881000012
2340657.48900001617151.7440000182340583.81699999617110.290000021
2340573.28600003       617139.252340478.00087945617184.539181647

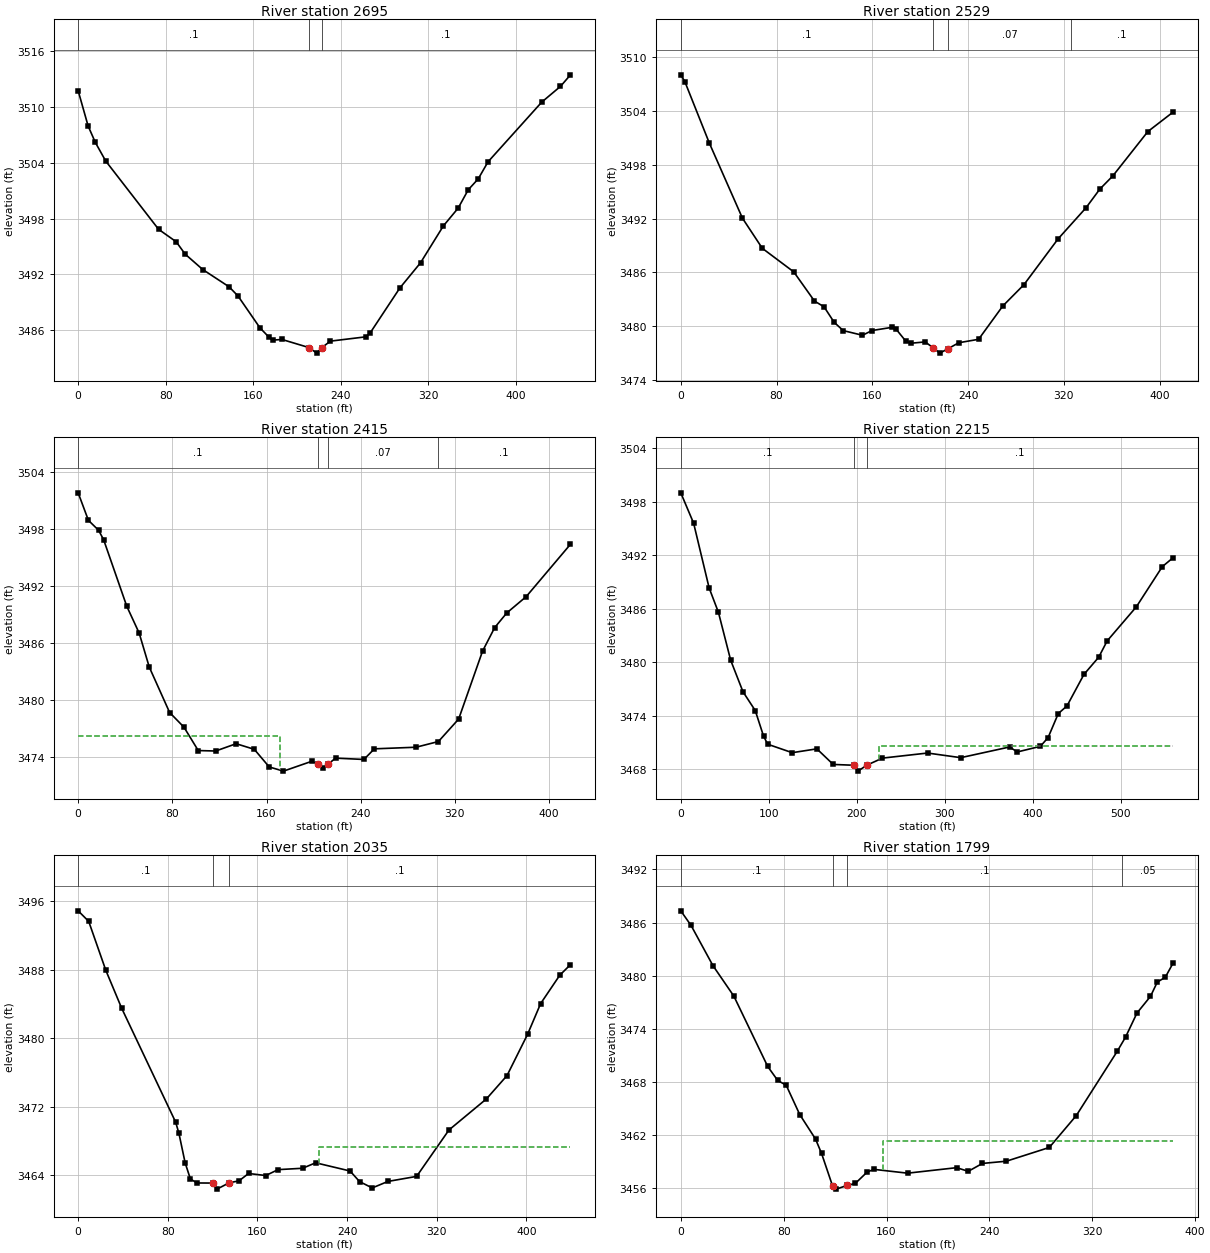
Type RM Length L Ch R = 1 ,2695    ,166,166,166
XS GIS Cut Line= 3
2341831.15001789616397.5158305772342139.77013709   616362.219964
2342262.68113606616296.881565206
#Sta/Elev= 30
       0 3511.74     9.1 3507.95    15.7 3506.18    25.2 3504.18    73.5 3496.84
    89.6  3495.5    97.7 3494.18   113.8 3492.52   137.9 3490.66     146 3489.68
   166.1 3486.25   174.2 3485.26   178.2 3484.93   186.2    3485   210.8 3484.13
     218 3483.53   222.5 3484.11   230.5 3484.82   262.7 3485.28   266.8  3485.7
   293.9 3490.53   312.8 3493.24   333.7 3497.21   347.2 3499.12   356.4 3501.09
   365.5 3502.26   374.5  3504.1   423.6 3510.52   440.7 3512.21449.8304 3513.45
#Mann= 3 ,-1,0
       0      .1       0   210.8    .045       0   222.5      .1       0
Bank Sta=210.8,222.5
XS Rating Curve= 0 ,0
Exp/Cntr(USF)=0,0
Exp/Cntr=0.3,0.1

Type RM Length L Ch R = 1 ,2529    ,113.6,113.6,113.6
XS GIS Cut Line= 5
2341860.76484318616530.4392925752342029.17439363616518.748781962
2342135.19082505616502.0936759782342207.02039294 616457.20348367
2342250.18267067616431.089152998
#Sta/Elev= 30
       0 3508.01     3.4 3507.25    23.9 3500.39    51.5 3492.04    68.1 3488.68
    94.4 3486.05   111.7  3482.8   119.7 3482.16   128.1 3480.44   135.7 3479.51
   151.8 3478.99   159.8 3479.52   176.3 3479.87     180 3479.65     188 3478.33
   192.1  3478.1   204.2 3478.25 211.0063477.574   216.4    3477223.52183477.511
   232.3 3478.16   248.8 3478.54     269 3482.25   286.7 3484.63   315.2 3489.73
   338.5 3493.19   350.1 3495.28   360.9 3496.74   390.2 3501.69   411.3 3503.86
#Mann= 4 ,-1,0
       0      .1       0 211.006    .045       0223.5218     .07       0
  326.13      .1       0
Bank Sta=211.006,223.5218
XS Rating Curve= 0 ,0
Exp/Cntr(USF)=0,0
Exp/Cntr=0.3,0.1

Type RM Length L Ch R = 1 ,2415    ,199.7,199.7,199.7
XS GIS Cut Line= 4
2341880.10347693616597.8024214522341954.66995058616627.750709213
2342178.40213645616604.3696879872342266.30340181616533.601660744
#Sta/Elev= 30
       0 3501.84     8.7 3498.94    17.3  3497.9    21.6 3496.91    41.3 3489.88
    51.8 3487.06    60.4 3483.47    77.7 3478.68    89.9 3477.13     102 3474.67
   116.8 3474.62   134.2 3475.39   149.6  3474.8   162.3 3472.94   174.4  3472.5
   198.5 3473.54203.68873473.262   207.9 3472.83  212.62 3473.26   218.6 3473.87
   242.7 3473.73   251.6 3474.85     287 3475.02     306 3475.62   323.2 3477.99
   343.5 3485.15   353.8 3487.63   364.1 3489.18   380.6  3490.9   418.2 3496.42
#Mann= 4 ,-1,0
       0      .1       0203.6887    .045       0  212.62     .07       0
  305.31      .1       0
#XS Ineff= 2 , 0
          171.22 3476.16
Permanent Ineff=
       F       F
Bank Sta=203.6887,212.62
XS Rating Curve= 0 ,0
Exp/Cntr(USF)=0,0
Exp/Cntr=0.3,0.1

Type RM Length L Ch R = 1 ,2215    ,180.5,180.5,180.5
XS GIS Cut Line= 3
 2341883.4568029616653.6887057282342295.52791192616899.866376225
2342364.41123681 616939.25753426
#Sta/Elev= 30
       0 3498.99    14.6 3495.58    32.2 3488.32    42.8 3485.57    56.7  3480.2
    70.7 3476.66    84.6 3474.56      94  3471.7    98.7 3470.78   126.6 3469.83
   154.6 3470.26   173.2 3468.51   196.5 3468.42   201.4 3467.76  211.18 3468.42
   229.1 3469.22   280.4 3469.79   318.1 3469.27   373.6 3470.47   382.3 3469.91
   408.5 3470.54   417.3 3471.52   428.9 3474.22   438.8 3475.08   458.1 3478.62
   474.8 3480.54   484.4 3482.37   517.6  3486.2   547.1 3490.71559.3572 3491.71
#Mann= 3 ,-1,0
       0      .1       0   196.5    .045       0  211.18      .1       0
#XS Ineff= 2 , 0
                          225.38         3470.55
Permanent Ineff=
       F       F
Bank Sta=196.5,211.18
XS Rating Curve= 0 ,0
Exp/Cntr(USF)=0,0
Exp/Cntr=0.3,0.1

Type RM Length L Ch R = 1 ,2035    ,236.2,236.2,236.2
XS GIS Cut Line= 2
2341848.13482852616750.2452978222342146.65751784617072.748352998
#Sta/Elev= 30
       0 3494.89     9.4 3493.66    24.7 3487.93    38.9 3483.48      87 3470.18
    89.9 3468.89    95.5 3465.41   100.2 3463.52   106.1 3463.06  120.05 3463.05
   123.9 3462.34   134.8 3463.08   143.6 3463.31   152.1 3464.17   167.5 3463.93
   178.4 3464.62   200.3 3464.78     212 3465.42   242.7 3464.46   251.2 3463.22
   262.5 3462.48   276.5 3463.24   302.1 3463.83     331 3469.26   364.4 3472.89
   382.8 3475.62   401.2 3480.46   412.8 3484.04   429.9 3487.36439.4588  3488.6
#Mann= 3 ,-1,0
       0      .1       0  120.05    .045       0   134.8      .1       0
#XS Ineff= 2 , 0
                          214.81         3467.21
Permanent Ineff=
       F       F
Bank Sta=120.05,134.8
XS Rating Curve= 0 ,0
Exp/Cntr(USF)=0,0
Exp/Cntr=0.3,0.1

Type RM Length L Ch R = 1 ,1799    ,214,214,214
XS GIS Cut Line= 3
2341718.83078184616869.6343058722341743.86271357   616938.661754
2341944.11816748 617174.56874705
#Sta/Elev= 30
       0 3487.32       8 3485.67      25 3481.14    41.3 3477.69    67.6 3469.76
    75.4 3468.18      82 3467.64    92.5 3464.34   104.8 3461.57   109.5 3459.94
     118  3456.3   120.8 3455.92   129.4 3456.34   135.7 3456.56   144.9 3457.84
   150.2 3458.15   176.4 3457.72   214.5 3458.34   223.6 3457.93   234.6 3458.82
   253.2 3459.07   286.6 3460.62   307.6 3464.22   339.4 3471.46   345.9 3473.07
   354.8 3475.79   365.3 3477.67   370.6 3479.28   376.8 3479.82   382.9 3481.43
#Mann= 4 ,-1,0
       0      .1       0     118    .045       0   129.4      .1       0
  343.43     .05       0
#XS Ineff= 2 , 0
                          157.38         3461.35
Permanent Ineff=
       F       F
Bank Sta=118,129.4
XS Rating Curve= 0 ,0
Exp/Cntr(USF)=0,0
Exp/Cntr=0.3,0.1

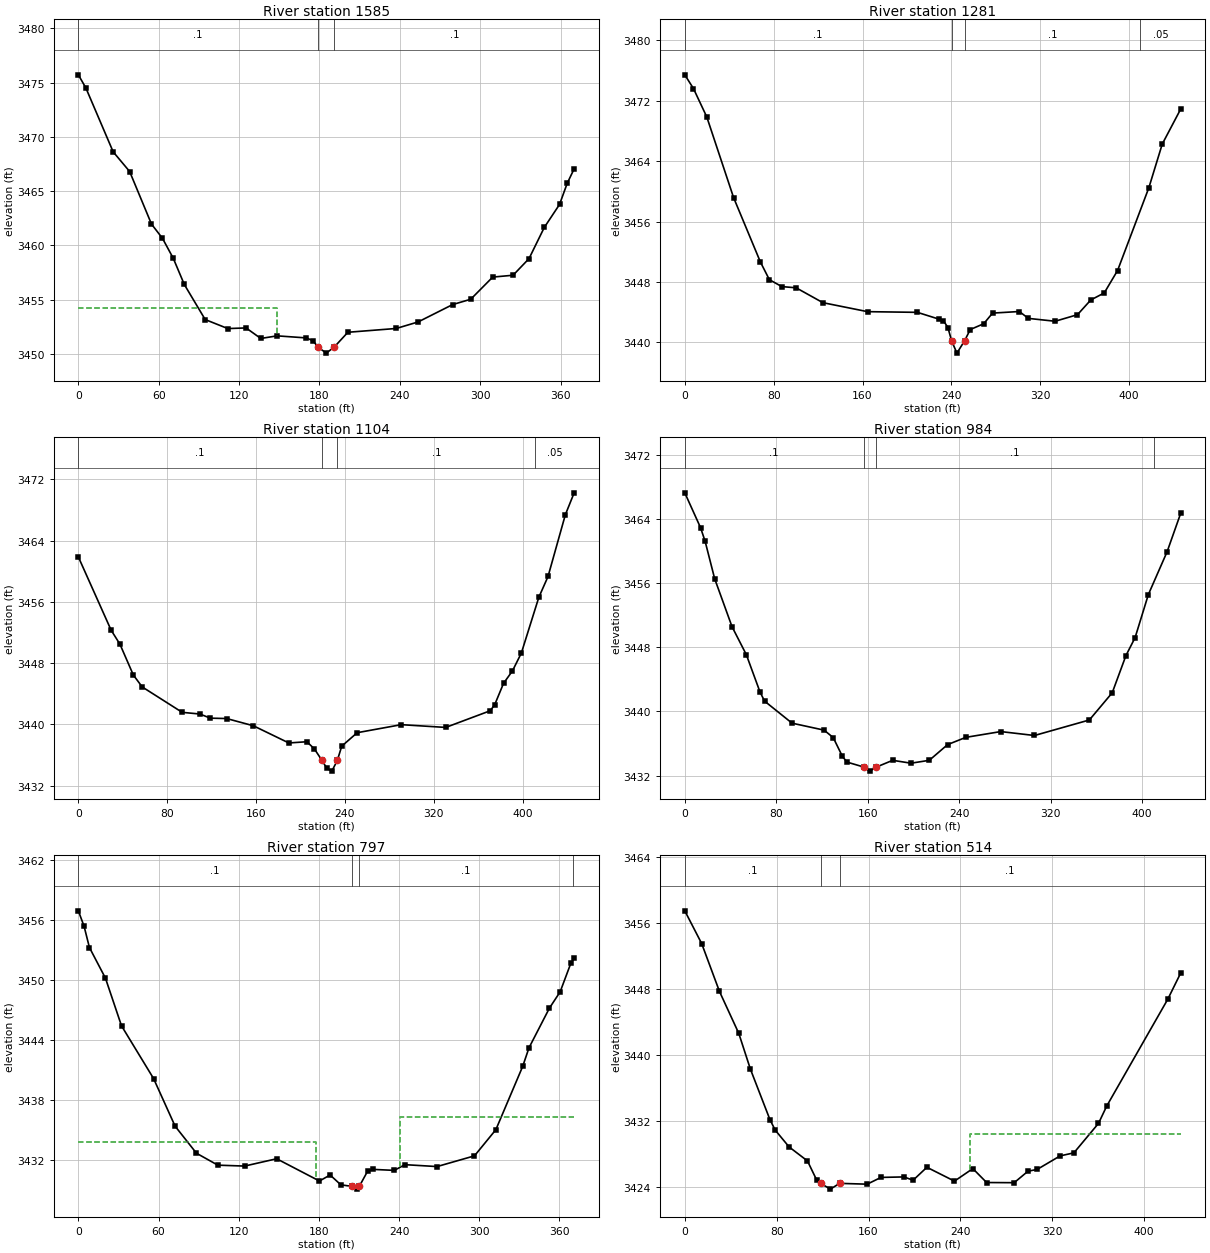
Type RM Length L Ch R = 1 ,1585    ,303.6,303.6,303.6
XS GIS Cut Line= 4
  2341602.181564616955.6646156192341634.53078451 617115.91767724
2341689.27561923617183.104519845 2341784.3325595617256.263526237
#Sta/Elev= 30
       0 3475.71     5.6 3474.51      26 3468.62    38.3 3466.81    54.6 3461.97
    62.8 3460.66    70.9 3458.81    79.1 3456.41    94.7 3453.18   111.6 3452.35
   125.2 3452.41   136.2 3451.44   148.4 3451.68   170.3 3451.49   175.4 3451.21
   178.8 3450.65   185.1 3450.09   191.1 3450.66   201.2 3452.01   237.3 3452.36
   253.6 3452.96   279.4 3454.56   292.9 3455.05   309.3 3457.09   324.5 3457.26
   336.4 3458.79   347.8 3461.66   359.2 3463.78   364.9 3465.72   370.1 3467.06
#Mann= 3 ,-1,0
       0      .1       0   178.8    .045       0   191.1      .1       0
#XS Ineff= 2 , 0
          148.56 3454.22
Permanent Ineff=
       F       F
Bank Sta=178.8,191.1
XS Rating Curve= 0 ,0
Exp/Cntr(USF)=0,0
Exp/Cntr=0.3,0.1

Type RM Length L Ch R = 1 ,1281    ,177.2,177.2,177.2
XS GIS Cut Line= 2
2341395.73251984616937.4534528792341352.74839463617381.622746691
#Sta/Elev= 30
       0 3475.44     7.8 3473.62    19.8 3469.86    43.9 3459.19      68 3450.67
    76.1 3448.32    87.3  3447.4   100.2 3447.24   124.3 3445.27   164.5 3444.08
   209.3 3443.99   228.8 3443.09   232.8 3442.88   236.8 3441.98  240.13 3440.22
   244.9 3438.59  251.79 3440.22   256.9 3441.71     269 3442.48     277 3443.89
   301.1  3444.1   309.2 3443.19   333.3 3442.81   353.4 3443.68   365.4 3445.63
   377.5 3446.56   389.5 3449.53   417.7 3460.51   429.7 3466.27446.2443 3470.89
#Mann= 4 ,-1,0
       0      .1       0  240.13    .045       0  251.79      .1       0
     410     .05       0
Bank Sta=240.13,251.79
XS Rating Curve= 0 ,0
Exp/Cntr(USF)=0,0
Exp/Cntr=0.3,0.1

Type RM Length L Ch R = 1 ,1104    ,119.7,119.7,119.7
XS GIS Cut Line= 4
2341212.93292854 616931.647318322341213.86940186617135.798501223
2341192.33051559617177.9398004462341187.64814901617372.726250188
#Sta/Elev= 30
       0 3461.87    29.5  3452.3    37.5 3450.45    49.5 3446.44    57.5 3444.88
    93.5 3441.56   109.5 3441.34   118.8  3440.8   133.5 3440.75   157.5 3439.81
   189.5 3437.56   205.7 3437.72   212.4  3436.8   219.2 3435.31   223.7 3434.25
   228.2 3433.88  233.15 3435.28   237.1 3437.14     251  3438.9   290.7 3439.95
   330.7 3439.59   370.8 3441.77   374.8 3442.56   382.8 3445.36   390.8 3446.98
   398.8 3449.31   414.5 3456.58   422.8 3459.31   438.4 3467.38446.3227 3470.24
#Mann= 4 ,-1,0
       0      .1       0   219.2    .045       0  233.15      .1       0
  411.48     .05       0
Bank Sta=219.2,233.15
XS Rating Curve= 0 ,0
Exp/Cntr(USF)=0,0
Exp/Cntr=0.3,0.1

Type RM Length L Ch R = 1 ,984     ,187,187,187
XS GIS Cut Line= 2
2341104.30202388616935.3932115842341108.04791714617368.980356924
#Sta/Elev= 30
       0 3467.31    13.8 3462.95    17.8 3461.24    26.1 3456.59    41.3 3450.59
    53.8  3447.1    65.8 3442.42    69.8 3441.29    93.8 3438.54   121.8 3437.67
   129.8 3436.74   137.8  3434.4   141.8 3433.68   156.3 3433.07   161.8 3432.55
   167.4 3433.05   181.8  3433.9   197.8 3433.54   213.8  3433.9   229.8 3435.86
   245.8 3436.77   276.3 3437.49   305.8    3437   353.8 3438.94   373.8 3442.34
   385.8 3446.99   393.8 3449.23   405.4 3454.61   421.8 3459.96433.6033 3464.73
#Mann= 4 ,-1,0
       0      .1       0   156.3    .045       0   167.4      .1       0
     410     .05       0
Bank Sta=156.3,167.4
XS Rating Curve= 0 ,0
Exp/Cntr(USF)=0,0
Exp/Cntr=0.3,0.1

Type RM Length L Ch R = 1 ,797     ,283.2,283.2,283.2
XS GIS Cut Line= 2
2340967.57691973616972.8521442272340977.87812621 617343.69557739
#Sta/Elev= 30
       0 3456.89     4.3 3455.35     8.3 3453.23    20.3 3450.17    32.3 3445.42
    56.3 3440.16    72.4 3435.41    88.4 3432.71   104.4 3431.52   124.4 3431.43
   148.4 3432.16   180.4 3429.94   188.4 3430.54   196.4 3429.56   204.4 3429.41
   208.4 3429.13  210.24 3429.41   216.4 3430.91   220.4  3431.1   236.4    3431
   244.4 3431.57   268.4 3431.38   296.4 3432.45   312.4 3435.06   332.5 3441.38
   337.2 3443.23   352.5 3447.19   360.5 3448.81   368.5 3451.66370.9865 3452.15
#Mann= 4 ,-1,0
       0      .1       0   204.4    .045       0  210.24      .1       0
     370     .05       0
#XS Ineff= 2 , 0
          177.73 3433.88  240.81         3436.34
Permanent Ineff=
       F       F
Bank Sta=204.4,210.24
XS Rating Curve= 0 ,0
Exp/Cntr(USF)=0,0
Exp/Cntr=0.3,0.1

Type RM Length L Ch R = 1 ,514     ,282.1,282.1,282.1
XS GIS Cut Line= 4
 2340860.8189617616948.5038380092340823.36002906617013.120496818
2340830.85181558617299.681331535 2340860.8189617617363.361517027
#Sta/Elev= 30
       0 3457.49    14.7 3453.52    30.2 3447.71      47 3442.63    57.1  3438.3
    74.1 3432.18    78.7  3430.9    90.8 3428.86   106.8 3427.16   114.8 3424.85
  118.23 3424.44   126.8 3423.74   134.8 3424.44   158.8 3424.34   170.8 3425.16
   190.8 3425.22   198.8 3424.82   210.8 3426.39   234.8 3424.71   250.8 3426.23
   262.8 3424.54   286.8 3424.52   298.8 3425.91   306.8 3426.13   326.8 3427.77
   338.8 3428.14   360.2 3431.71   367.4 3433.82   420.5 3446.76 431.727 3449.93
#Mann= 3 ,-1,0
       0      .1       0  118.23    .045       0   134.8      .1       0
#XS Ineff= 2 , 0
                          248.63         3430.45
Permanent Ineff=
       F       F
Bank Sta=118.23,134.8
XS Rating Curve= 0 ,0
Exp/Cntr(USF)=0,0
Exp/Cntr=0.3,0.1

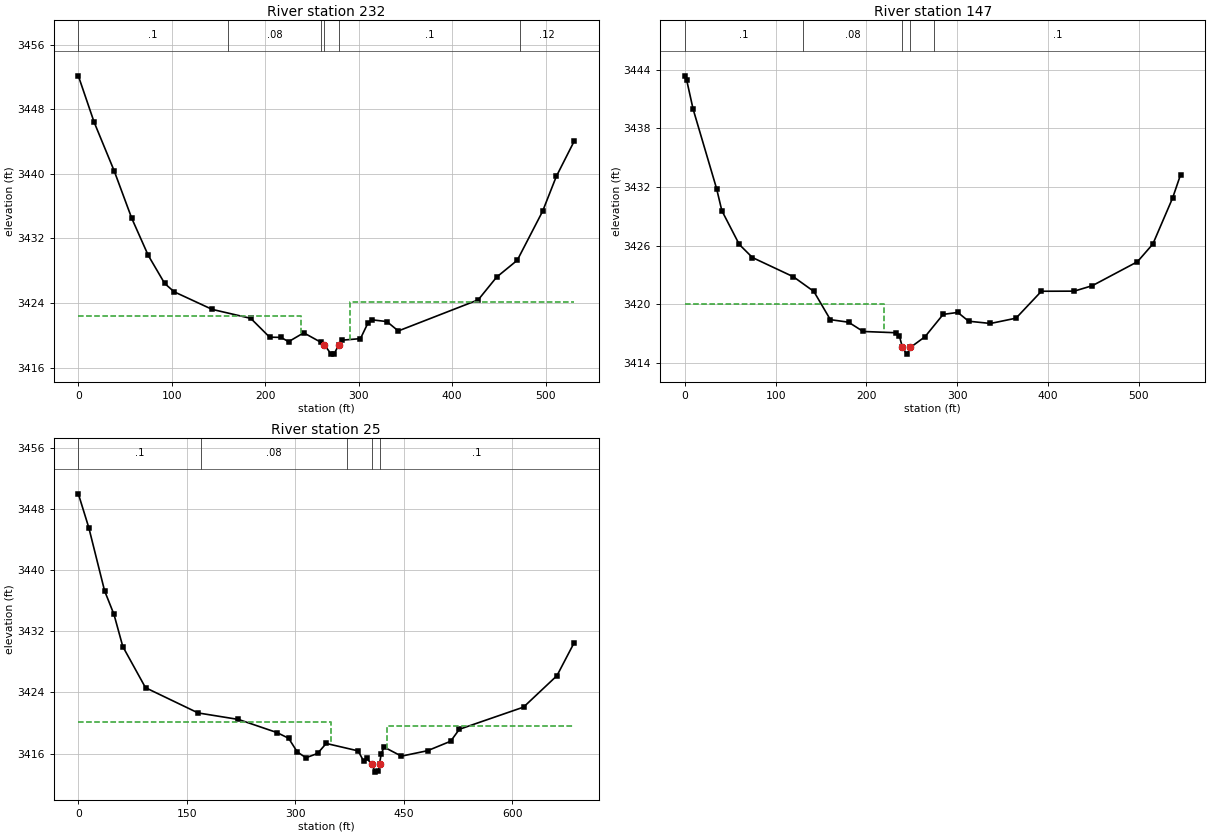
Type RM Length L Ch R = 1 ,232     ,84.5,84.5,84.5
XS GIS Cut Line= 4
2340747.50569045616915.7272719472340644.49362569 617050.57942946
2340679.14313838617270.6506587362340749.37863709617389.582769877
#Sta/Elev= 30
       0 3452.13    16.9 3446.39    38.4 3440.35    57.2 3434.48    74.8  3429.9
    92.4 3426.42   102.5 3425.39   143.2 3423.21   184.5  3422.1   204.7 3419.77
   216.9 3419.74     225 3419.21   241.2 3420.31   259.7 3419.13  263.38 3418.82
   270.5 3417.67   273.6 3417.68  278.73 3418.81   281.7 3419.39   301.9 3419.59
     310 3421.54   314.1 3421.92   330.2  3421.7   342.4 3420.54   427.9 3424.39
   447.6  3427.2   469.7 3429.29   496.8 3435.35   511.5 3439.67530.6005 3444.03
#Mann= 6 ,-1,0
       0      .1       0     160     .08       0   259.7      .1       0
  263.38    .045       0  278.73      .1       0  472.48     .12       0
#XS Ineff= 2 , 0
           238.1 3422.39  290.71         3424.17
Permanent Ineff=
       F       F
Bank Sta=263.38,278.73
XS Rating Curve= 0 ,0
Exp/Cntr(USF)=0,0
Exp/Cntr=0.3,0.1

Type RM Length L Ch R = 1 ,147     ,122.2,122.2,122.2
XS GIS Cut Line= 4
 2340671.0983064616895.4408641662340584.39679737617023.786405088
2340604.19477975617341.2368121542340652.66570212617395.851935951
#Sta/Elev= 30
       0 3443.38     2.1 3442.93     9.1 3439.99      35 3431.83    40.8 3429.57
      60 3426.11    74.5 3424.77   119.6  3422.8   142.1  3421.3   160.3 3418.41
   180.3 3418.15   196.4  3417.2   232.4 3417.07   236.4 3416.71  239.63 3415.57
   244.5 3414.88   248.5 3415.57   264.5 3416.66   284.5 3418.95   300.6 3419.15
   312.6 3418.25   336.6 3418.02   364.7 3418.56   392.7 3421.32   428.8 3421.33
   448.8 3421.89   498.4 3424.34   515.4 3426.15   537.1 3430.85     546 3433.27
#Mann= 5 ,-1,0
       0      .1       0     130     .08       0  239.63    .045       0
   248.5     .08       0  274.89      .1       0
#XS Ineff= 2 , 0
          219.79 3419.98
Permanent Ineff=
       F       F
Bank Sta=239.63,248.5
XS Rating Curve= 0 ,0
Exp/Cntr(USF)=0,0
Exp/Cntr=0.3,0.1

Type RM Length L Ch R = 1 ,25      ,,,
XS GIS Cut Line= 4
2340615.55228308 616802.765918012340497.55664525617001.672850343
2340506.82773108617305.0902047492340598.69576339617424.771494542
#Sta/Elev= 30
       0 3449.96    14.5 3445.53    36.3 3437.28    49.3 3434.19    61.5 3429.99
    92.9 3424.61   165.6 3421.31   221.4 3420.46   274.8 3418.74   290.8    3418
   302.8 3416.21   314.8 3415.45   330.8 3416.01   342.8 3417.32   386.9 3416.35
   394.9 3414.96   398.9 3415.36   405.6 3414.64   410.9 3413.57   414.9 3413.67
  416.57 3414.65   418.9 3415.98   422.9 3416.84   446.8 3415.66   482.9 3416.37
   514.9 3417.61   526.9 3419.17   615.7 3422.07   661.9 3426.18685.7067 3430.49
#Mann= 5 ,-1,0
       0      .1       0     170     .08       0  371.27      .1       0
   405.6    .045       0  416.57      .1       0
#XS Ineff= 2 , 0
          349.01 3420.15  426.96         3419.65
Permanent Ineff=
       F       F
Bank Sta=405.6,416.57
XS Rating Curve= 0 ,0
Exp/Cntr(USF)=0,0
Exp/Cntr=0.3,0.1
LCMann Table=0

Chan Stop Cuts=-1
Use User Specified Reach Order=0
Composite Channel Slope=5